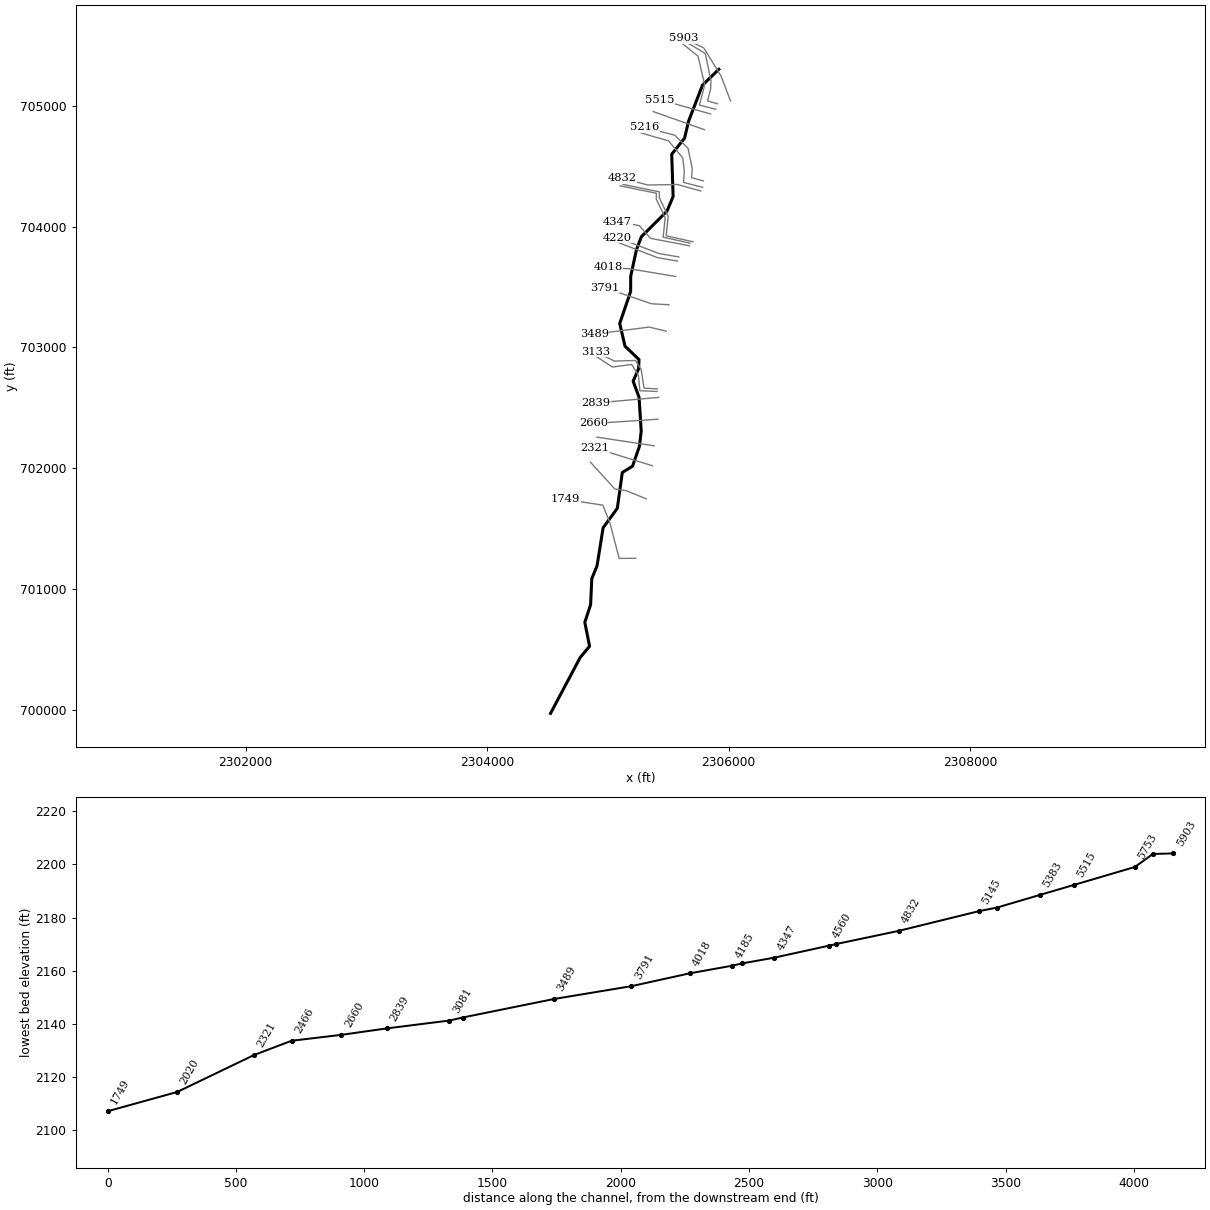
--- ISNERCK_U.prj (project) ---

Proj Title=ISNERCK_U
Current Plan=p01
Default Exp/Contr=0,0
English Units
Geom File=g01
Flow File=f01
Plan File=p01
BEGIN DESCRIPTION:
----------MODEL BY WSP USA 2022----------
AFH study
Randolph County, WV
HEC-RAS Version: RAS 6.2
Vertical Datum: NAVD88
Projection: NAD 1983 StatePlane West Virginia S FIPS 4702 (US Feet)
Terrain: 1-meter LIDAR (FEMA Region III 3DEP collected 2016-2018)
Land Use: 2019 NLCD
Hydrologic Method:
WV SIR2010-5033 regression equations
Additional Model Notes:
Formerly ISNERCK
Model was split at confluence with POERN; this model is the upper reach.
KWSEL tie-in due to coincident peak
END DESCRIPTION:
DSS Export Rating Curves= 0
DSS Export Rating Curve Sorted= 0
DSS Export Volume Flow Curves= 0
DXF OffsetX= 0
DXF OffsetY= 0
DXF ScaleX= 0
DXF ScaleY= 0

--- ISNERCK_U.p01 (plan) ---

Plan Title=Floodplain
Program Version=6.20
Short Identifier=Floodplain
Geom File=g01
Flow File=f01
Subcritical Flow
K Sum by GR= 0
Std Step Tol= 0.01
Critical Tol= 0.01
Num of Std Step Trials= 20
Max Error Tol= 0.3
Flow Tol Ratio= 0.001
Split Flow NTrial= 30
Split Flow Tol= 0.02
Split Flow Ratio= 0.02
Log Output Level= 0
Friction Slope Method= 1
Unsteady Friction Slope Method= 2
Unsteady Bridges Friction Slope Method= 1
Parabolic Critical Depth
Global Vel Dist= 0 , 0 , 0
Global Log Level= 0
CheckData=True
Encroach Param=-1 ,0,0, 0
Mapping Interval=1HOUR
Computation Time Step Use Courant=        0
Computation Time Step Use Time Series=    0
Computation Time Step Count To Double=0
Computation Time Step Max Doubling=0
Computation Time Step Max Halving=0
Computation Time Step Residence Courant=0
Run HTab= 0
Run UNet= 0
Run Sediment= 0
Run PostProcess= 0
Run WQNet= 0
Run RASMapper=-1
UNET Theta= 0
UNET Theta Warmup= 0
UNET ZTol= 0
UNET ZSATol= 0
UNET MxIter= 0
UNET Max Iter WO Improvement= 0
UNET MaxInSteps= 0
UNET DtIC= 0
UNET DtMin= 0
UNET MaxCRTS= 0
UNET WFStab= 0
UNET SFStab= 0
UNET WFX= 1
UNET SFX= 1
UNET Gravity=32.174
UNET 1D Methodology=Finite Difference
UNET DSS MLevel= 1
UNET Pardiso=0
UNET DZMax Abort= 0
UNET Use Existing IB Tables= 0
UNET Froude Reduction=False
UNET Froude Limit= 0
UNET Froude Power= 0
UNET D1 Cores= 0
UNET WindReference=Eulerian
UNET WindDragFormulation=Hsu (1988)
UNET D2 Coriolis=0
UNET D2 Cores= 0
UNET D2 Theta= 1
UNET D2 Theta Warmup= 1
UNET D2 Z Tol= 0.01
UNET D2 Volume Tol= 0.01
UNET D2 Max Iterations= 20
UNET D2 Equation= 0
UNET D2 RampUpFraction=0.1
UNET D2 TimeSlices= 1
UNET D2 Turbulence Formulation=Non-Conservative (original)
UNET D2 Eddy Viscosity=0.3
UNET D2 Transverse Eddy Viscosity=0.1
UNET D2 Smagorinsky Mixing=0
UNET D2 BCVolumeCheck=0
UNET D2 Cores=0
UNET D2 SolverType=PARDISO (Direct)
UNET D2 Minimum Iterations= 2147483647
UNET D2 Maximum Iterations= 2147483647
UNET D2 Restart Number= 10
UNET D2 Relaxation Coeff=1.3
UNET D2 SOR Precondition Iterations= 10
UNET D2 ILUT Maximum Fill= 8
UNET D2 ILUT Tolerance=1E-08
UNET D1D2 MaxIter= 0
UNET D1D2 ZTol=0.01
UNET D1D2 QTol=0.1
UNET D1D2 MinQTol=1
Write IC File= 0
Write IC File at Fixed DateTime=0
Write IC File at Sim End=0
Echo Input=False
Echo Parameters=False
Echo Output=False
Write Detailed= 0
HDF Write Warmup=0
HDF Write Time Slices=0
HDF Flush=0
HDF Compression= 1
HDF Chunk Size= 1
HDF Spatial Parts= 1
HDF Use Max Rows=0
HDF Fixed Rows= 1
Calibration Method= 0
Calibration Iterations= 20
Calibration Max Change=0.05
Calibration Tolerance=0.2
Calibration Maximum=1.5
Calibration Minimum=0.5
Calibration Optimization Method= 1
WQ AD Non Conservative
WQ ULTIMATE=-1
WQ Max Comp Step=1HOUR
WQ Output Interval=15MIN
WQ Output Selected Increments= 0
WQ Output face flow=0
WQ Output face velocity=0
WQ Output face area=0
WQ Output face dispersion=0
WQ Output cell volume=0
WQ Output cell surface area=0
WQ Output cell continuity=0
WQ Output cumulative cell continuity=0
WQ Output face conc=0
WQ Output face dconc_dx=0
WQ Output face courant=0
WQ Output face peclet=0
WQ Output face adv mass=0
WQ Output face disp mass=0
WQ Output cell mass=0
WQ Output cell source sink temp=0
WQ Output nsm pathways=0
WQ Output nsm derived pathways=0
WQ Create Restart=0
WQ Fixed Restart=0
WQ System Summary=0
WQ Write To DSS=0
Sorting and Armoring Iterations= 10
XS Update Threshold= 0.02
Bed Roughness Predictor= 0
Hydraulics Update Threshold= 0.02
Energy Slope Method= 1
Volume Change Method= 1
Sediment Retention Method= 0
Sediment TS Multiplier= 1
Warm Up Method= 0
XS Weighting Method= 0
Number of US Weighted Cross Sections= 1
Number of DS Weighted Cross Sections= 1
Upstream XS Weight=0
Main XS Weight=1
Downstream XS Weight=0
Number of DS XS's Weighted with US Boundary= 1
Upstream Boundary Weight= 1
Weight of XSs Associated with US Boundary= 0
Number of US XS's Weighted with DS Boundary= 1
Downstream Boundary Weight= 0.5
Weight of XSs Associated with DS Boundary= 0.5
Percentile Method= 0
Sediment Output Level= 3
Mass or Volume Output= 0
Output Increment Type= 1
Profile and TS Output Increment= 1
Transport Output Increment 1
XS Output Flag= 0
XS Output Increment= 10
Read HDF5 Sediment Hotstart= 0
Sediment Hotstart Type= 0
Write Gradation File= 0
Read Gradation Hotstart= 0
Write HDF5 File= 1
Write Binary Output= 1
Write DSS Sediment File= 0
DSS Sediment Output Type= 1
SV Curve= 0
Specific Gage Flag= 0
Subcell Erosion Methods= 0
Subcell Deposition Methods= 0
Advection Scheme= 1
Matrix Solver= 0
Implicit Weighting Factor= 1
Maximum Outer Loop Convergence Iterations= 5
Convergence Maximum Absolute= 0.001
Convergence RMSE= 0.0001
Grain Fractions Max Abs Error= 0.001
Max Subgrid Regions= 1
Max Subgrid Length Scale= 3.402823E+38
Initial Layer Thickness= 3.402823E+38
Min Layer Thickness= 3.402823E+38
Max Layer Thickness= 3.402823E+38
Number of Layers= 5

--- ISNERCK_U.f01 (steady flow) ---

Flow Title=Flow
Program Version=6.20
Number of Profiles= 1
Profile Names=P100yr
River Rch & RM=ISNERCK_U,Main            ,5903
     331
River Rch & RM=ISNERCK_U,Main            ,4347
     368
River Rch & RM=ISNERCK_U,Main            ,2020
     409
River Rch & RM=ISNERCK_U,Main            ,16
     982
Boundary for River Rch & Prof#=ISNERCK_U,Main            , 1
Up Type= 0
Dn Type= 1
Dn Known WS=2067.5
DSS Import GetInterval= 0
DSS Import GetPeak= 0
DSS Import FillOption= 0

--- ISNERCK_U.g01 (geometry) ---

Geom Title=Geometry
Program Version=6.20

River Reach=ISNERCK_U       ,Main
Reach XY= 30
2305918.83294689705302.198588082     2305783.011      705169.846
     2305667.125      704869.065     2305635.355      704732.347
     2305528.636      704598.909     2305540.355      704249.082
     2305489.573      704127.121     2305277.768      703916.183
     2305236.969      703809.412     2305189.226      703588.959
     2305188.358      703461.756      2305098.08      703197.433
     2305141.917      703009.499      2305258.02      702898.353
      2305254.33      702821.999     2305209.191      702719.569
     2305258.237      702586.322     2305276.032      702305.506
     2305261.709      702181.374     2305204.381      702015.539
     2305119.566      701963.389     2305078.115      701666.617
     2304960.623      701506.002     2304910.146      701189.447
     2304866.917       701084.76     2304857.021      700869.134
     2304809.105      700723.117     2304848.455      700524.362
     2304770.563      700431.287     2304525.204      699968.733

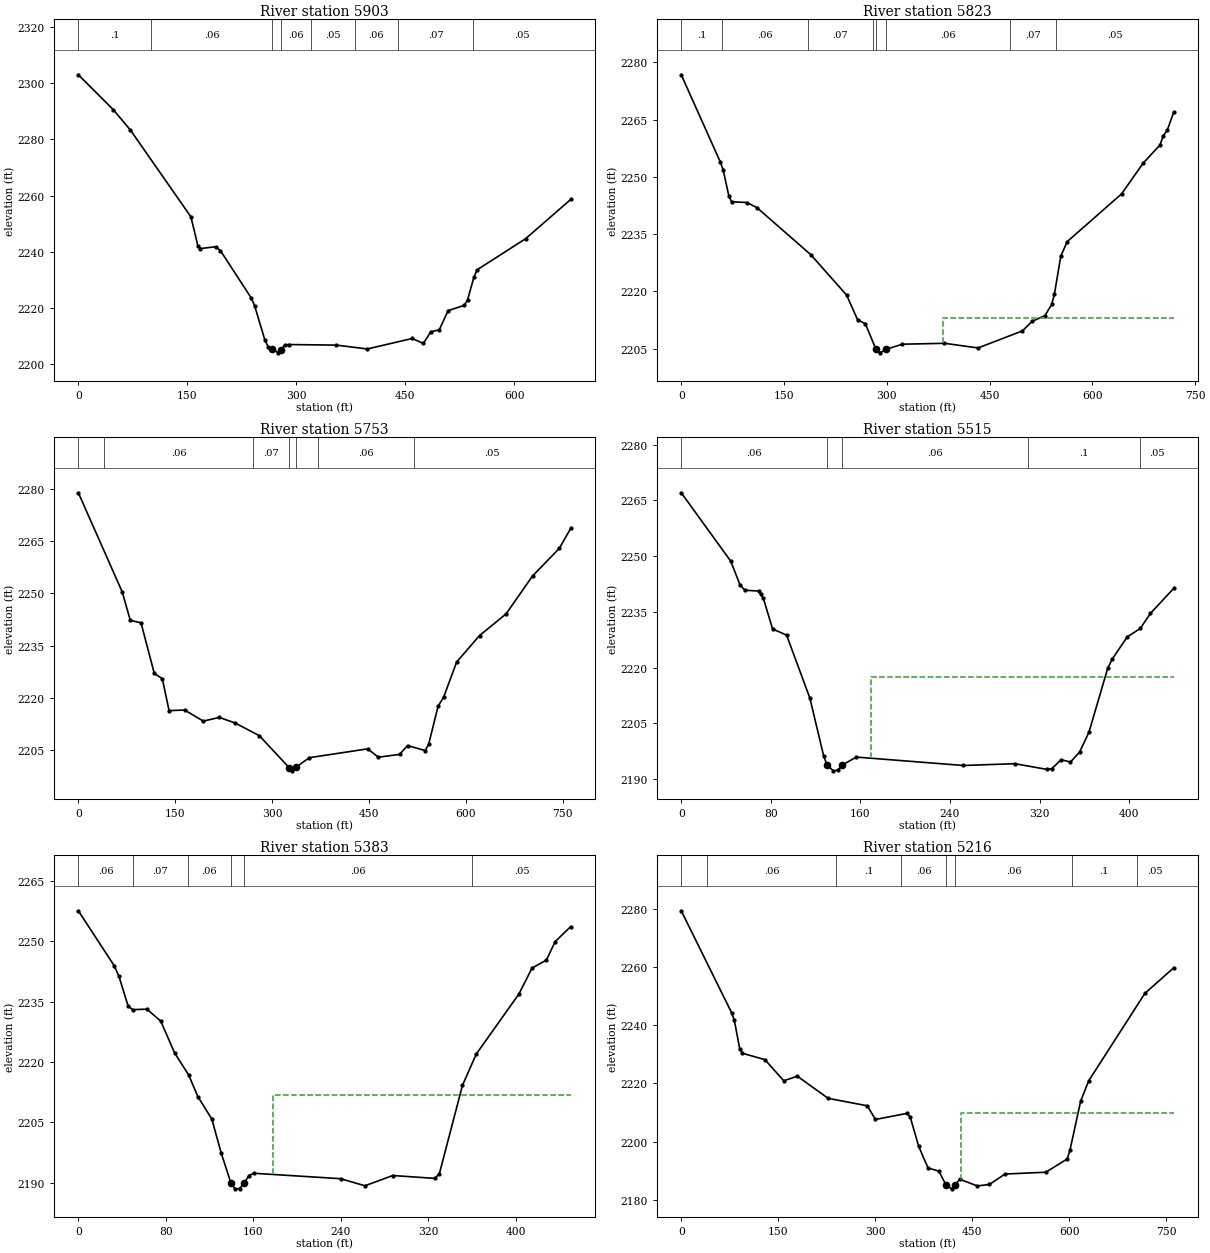
Type RM Length L Ch R = 1 ,5903    ,82.1,80.2,77
XS GIS Cut Line= 4
2306015.86955357 705040.358119082305937.23505843705246.017567911
2305794.75204159705478.5606048242305628.07379548705558.539279369
#Sta/Elev= 30
       0 2302.94      48 2290.57    71.7 2283.28     155 2252.45   164.6 2242.05
   167.9 2241.19   189.3 2241.84   195.6 2240.44     238 2223.62   242.7 2220.82
   256.7 2208.71   261.4 2206.26   266.9 2205.33   275.5 2204.13  278.98 2205.31
   284.3  2206.9   290.2 2207.08   355.2 2206.87   397.8 2205.51   459.6 2209.23
   474.9 2207.47     485 2211.56   496.8 2212.33   509.1 2219.14   531.3 2221.01
   535.7 2222.93   544.6 2231.08     549 2233.65   615.6 2244.68   677.8 2258.65
#Mann= 8 ,-1,0
       0      .1       0     100     .06       0   266.9    .045       0
  278.98     .06       0  320.18     .05       0  380.18     .06       0
  440.18     .07       0   542.9     .05       0
Bank Sta=266.9,278.98
XS Rating Curve= 0 ,0
Exp/Cntr(USF)=0,0
Exp/Cntr=0.3,0.1

Type RM Length L Ch R = 1 ,5823    ,69.7,70.1,72
BEGIN DESCRIPTION:
Structure XS 3
END DESCRIPTION:
XS GIS Cut Line= 6
2305907.02697672705016.8606486452305825.41261799  705039.8625482
 2305851.3858429705140.877010776 2305853.2297104  705210.9439756
2305806.21108927705433.1300087912305607.07339977 705552.98139599
#Sta/Elev= 30
       0 2276.78      57 2253.94    61.1  2251.9    69.5 2245.02    73.6 2243.51
    95.9 2243.31   110.6 2241.95   189.1 2229.63   241.4 2219.04   257.4 2212.57
   268.7 2211.54  284.18 2204.87   290.1 2203.92   299.1 2204.86   322.8 2206.18
   384.1 2206.42   433.2  2205.2     498 2209.67     512 2212.17   530.7 2213.64
   540.7 2216.62   544.7 2219.34     554 2229.27   563.4 2233.07   642.7 2245.58
   674.3 2253.65   698.8  2258.4   703.4 2260.76   709.3 2262.24   718.7 2266.93
#Mann= 8 ,-1,0
       0      .1       0      60     .06       0  184.79     .07       0
  279.19     .06       0  284.18    .045       0   299.1     .06       0
  479.19     .07       0  546.29     .05       0
#XS Ineff= 2 , 0
                          382.75         2213.03
Permanent Ineff=
       F       F
Bank Sta=284.18,299.1
XS Rating Curve= 0 ,0
Exp/Cntr(USF)=0,0
Exp/Cntr=0.3,0.1

Type RM Length L Ch R = 1 ,5753    ,232.4,238.2,242.9
BEGIN DESCRIPTION:
Structure XS 2
END DESCRIPTION:
XS GIS Cut Line= 6
2305894.02701598704970.7175171242305758.06501027705006.002967791
2305796.06981804705150.0963482532305799.75755303705181.442095674
 2305746.4500819705410.8793815882305586.26040466705540.155261464
#Sta/Elev= 30
       0  2278.9      68 2250.39    80.4 2242.24      97 2241.56   117.6 2226.99
     130 2225.49   140.5 2216.31   164.4  2216.5   193.4  2213.3   218.2 2214.37
     243 2212.75   280.3  2209.1  326.252199.971   330.5 2199.02   337.2 2200.09
   357.7  2202.8     448 2205.34   464.4 2202.94   497.3 2203.74   509.7 2206.28
   537.1 2204.84   542.5 2206.76     557 2217.61   565.5 2220.14   585.7 2230.28
   621.2 2237.89   662.3 2244.12   703.4 2255.04   744.6 2262.91   762.4  2268.7
#Mann= 7 ,-1,0
       0      .1       0      40     .06       0  270.47     .07       0
  326.25    .045       0   337.2     .07       0  371.05     .06       0
  519.36     .05       0
Bank Sta=326.25,337.2
XS Rating Curve= 0 ,0
Exp/Cntr(USF)=0,0
Exp/Cntr=0.3,0.1

Type RM Length L Ch R = 1 ,5515    ,132.7,132.1,131.6
BEGIN DESCRIPTION:
Structure XS 1
END DESCRIPTION:
XS GIS Cut Line= 2
2305850.70302829704932.1082318672305427.46009852705051.628660538
#Sta/Elev= 30
       0 2267.02    44.2 2248.63    52.5 2242.25    56.7 2240.83    69.1 2240.58
      71 2239.79    73.3 2238.67    81.6 2230.38    94.1 2228.74   114.9 2211.78
   127.3 2196.12  130.042193.928   135.8 2192.24   139.8 2192.39   143.9 2193.82
   156.4 2195.94     252 2193.68   297.9 2194.16   326.8 2192.62     331 2192.83
   339.3 2195.24   347.6  2194.6   355.9 2197.34   364.2 2202.68   380.9 2219.83
     385 2222.32   398.3 2228.26     410 2230.53   419.1 2234.59   439.8  2241.3
#Mann= 5 ,-1,0
       0     .06       0  130.04    .045       0   143.9     .06       0
     310      .1       0     410     .05       0
#XS Ineff= 2 , 0
                          169.68         2217.59
Permanent Ineff=
       F       F
Bank Sta=130.04,143.9
XS Rating Curve= 0 ,0
Exp/Cntr(USF)=0,0
Exp/Cntr=0.3,0.1

Type RM Length L Ch R = 1 ,5383    ,170.2,166.6,164.4
BEGIN DESCRIPTION:
Structure XS 4
END DESCRIPTION:
XS GIS Cut Line= 2
2305799.17262867704802.2961681242305374.82833258704952.316878865
#Sta/Elev= 30
       0 2257.54    32.9 2243.84    37.1 2241.26    45.6 2233.81    49.8 2232.99
    62.6 2233.11    75.3 2230.16      88 2222.24   100.8 2216.79   109.2 2211.42
     122 2205.83   130.5 2197.46   139.4 2189.98   143.2  2188.5   147.4 2188.57
   151.7 2189.98   155.9  2191.8   160.2 2192.37   239.7 2191.02     262 2189.26
   287.4 2191.81   325.6  2191.1   329.9 2192.16   351.1 2214.18   363.8    2222
   402.7 2236.87   414.7 2243.31   427.8 2245.29   435.9  2249.9   450.1 2253.62
#Mann= 6 ,-1,0
       0     .06       0      50     .07       0     100     .06       0
   139.4    .045       0   151.7     .06       0     360     .05       0
#XS Ineff= 2 , 0
                          177.62         2211.72
Permanent Ineff=
       F       F
Bank Sta=139.4,151.7
XS Rating Curve= 0 ,0
Exp/Cntr(USF)=0,0
Exp/Cntr=0.3,0.1

Type RM Length L Ch R = 1 ,5216    ,71.9,71.4,71.1
BEGIN DESCRIPTION:
Structure XS 3
END DESCRIPTION:
XS GIS Cut Line= 6
2305791.41560533704378.0775151862305693.05352282704404.775794726
2305698.67421325 704482.060288132305663.54489806704647.870655797
2305553.94143469704756.0689465632305305.22588319704822.112059109
#Sta/Elev= 30
       0 2279.27      78 2244.17    82.1 2241.62    90.4 2231.85    94.5 2230.33
   129.3 2228.13   158.5 2220.87   179.4 2222.45     227 2214.85   287.6 2212.28
   300.2 2207.58   349.6  2209.7   354.2 2208.26   367.1  2198.3   381.5 2190.91
   398.2 2189.83  409.15 2185.14   418.1 2183.75   423.7 2185.17   430.5 2187.04
   457.7 2184.75   476.4 2185.25   500.5 2188.83   563.6 2189.46   596.7 2194.01
     601 2197.13   617.4 2213.85   629.8 2220.83   716.7 2250.89   761.2 2259.67
#Mann= 8 ,-1,0
       0      .1       0      40     .06       0  239.41      .1       0
   340.1     .06       0  409.15    .045       0   423.7     .06       0
  603.82      .1       0  703.82     .05       0
#XS Ineff= 2 , 0
                          432.06         2209.83
Permanent Ineff=
       F       F
Bank Sta=409.15,423.7
XS Rating Curve= 0 ,0
Exp/Cntr(USF)=0,0
Exp/Cntr=0.3,0.1

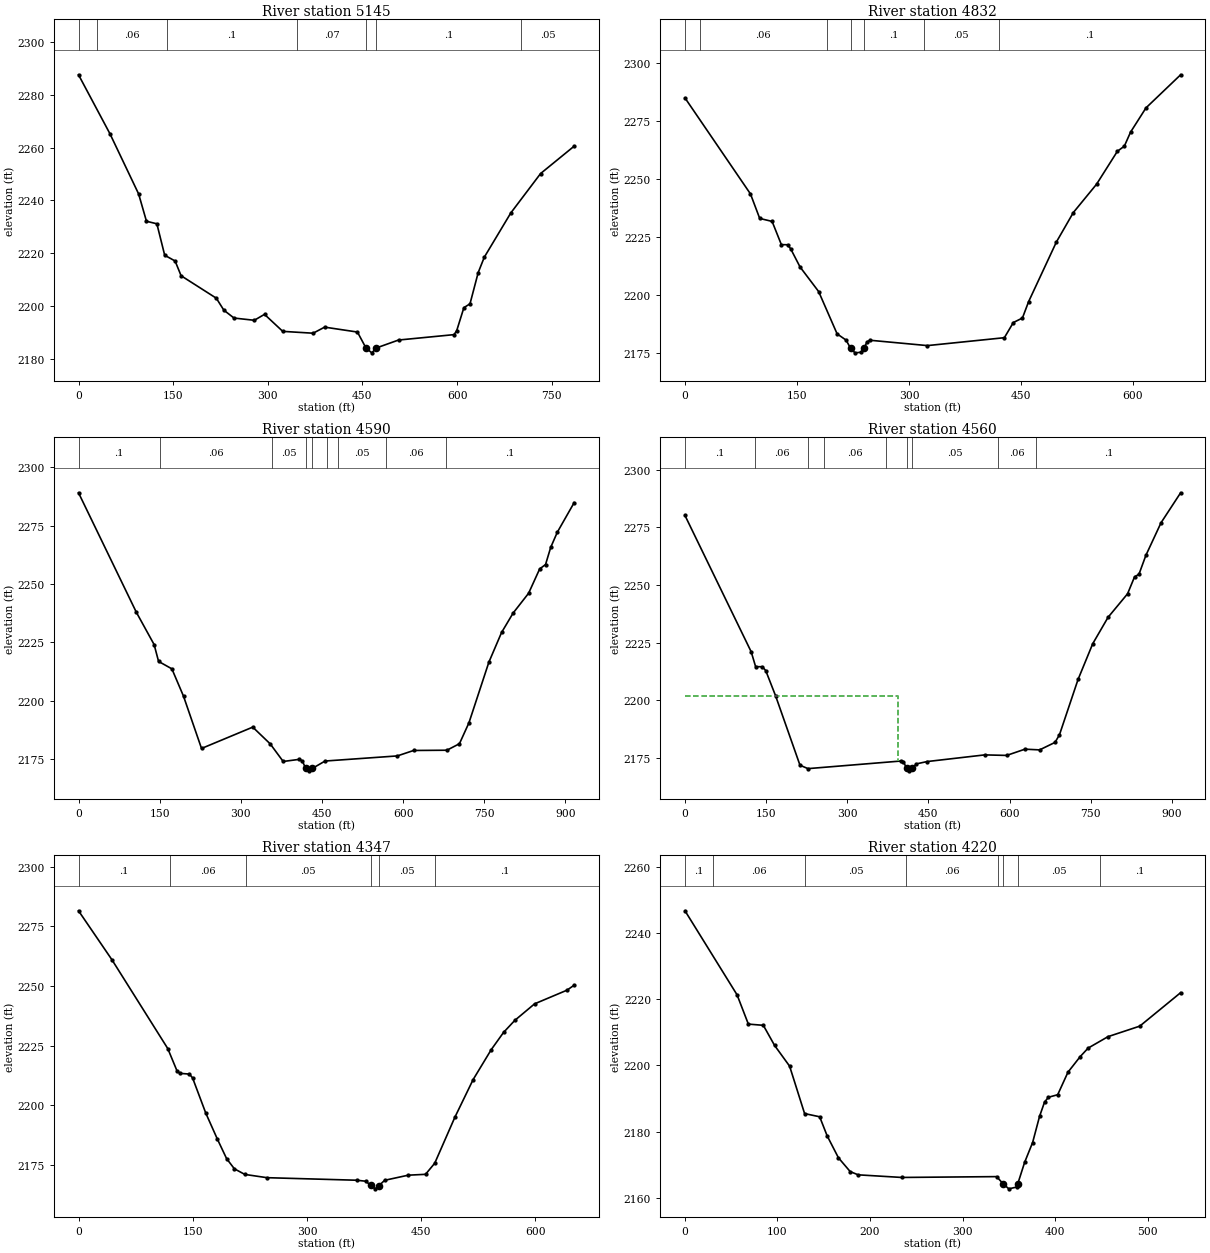
Type RM Length L Ch R = 1 ,5145    ,303.9,312.6,318
XS GIS Cut Line= 6
2305784.38974229704324.6809561072305627.01041027 704365.43096172
 2305632.6311007704459.5775264132305619.98454723704569.180989786
2305501.95004822704709.6982505212305277.12243104704774.336190459
#Sta/Elev= 30
       0 2287.51    49.8 2265.22    95.3 2242.45   107.7 2232.13   124.2 2231.17
   136.6 2219.28   153.1  2217.1   162.6 2211.53   218.4 2203.04   230.4  2198.5
   246.5 2195.53   278.6 2194.69   294.8 2196.93   323.7  2190.5   371.8  2189.8
   390.1  2192.1   442.1 2190.24  455.642184.205   464.8 2182.38   472.2 2184.24
   507.2 2187.22   595.1 2189.26   599.3 2190.67   610.8 2199.46   620.5 2200.92
   633.5 2212.73   643.2 2218.56   685.2 2235.28   732.4 2250.17   785.6 2260.52
#Mann= 7 ,-1,0
       0      .1       0      30     .06       0     140      .1       0
  346.88     .07       0  455.64    .045       0   472.2      .1       0
  701.64     .05       0
Bank Sta=455.64,472.2
XS Rating Curve= 0 ,0
Exp/Cntr(USF)=0,0
Exp/Cntr=0.3,0.1

Type RM Length L Ch R = 1 ,4832    ,250.5,242.7,235.6
XS GIS Cut Line= 4
2305768.63527006704294.698307231 2305575.7514991704348.277132496
2305331.43205589704343.9908264752305119.25990785 704399.71280475
#Sta/Elev= 30
       0  2285.1    87.7 2243.64   100.1 2233.04   116.7 2231.75   129.1 2221.72
   137.5 2221.66   141.6  2219.9   154.1 2212.08     179 2201.46   203.8 2183.14
   215.8 2180.46  221.922176.874   227.8 2174.96   235.8  2175.2   239.8 2176.92
   243.8 2179.69   247.8  2180.4   324.7 2178.09   427.8  2181.5   439.8 2188.05
     452 2190.01   460.3  2197.1   497.5 2222.86   520.2 2235.59   551.3 2247.83
   579.2 2262.06   588.5 2264.26   596.8 2270.31   617.5 2280.81   663.9 2295.11
#Mann= 7 ,-1,0
       0      .1       0      20     .06       0     190      .1       0
  221.92    .045       0   239.8      .1       0  320.19     .05       0
  420.19      .1       0
Bank Sta=221.92,239.8
XS Rating Curve= 0 ,0
Exp/Cntr(USF)=0,0
Exp/Cntr=0.3,0.1

Type RM Length L Ch R = 1 ,4590    ,29.2,29.6,30
XS GIS Cut Line= 6
2305704.64346959703874.2113726932305482.62619763703923.392413951
2305499.48826892704084.9872637962305426.41929334704236.745905389
2305426.41929334704287.3321192542305125.71235536704349.159713977
#Sta/Elev= 30
       0  2289.1     107 2237.89   139.8 2224.08     148 2216.88   172.6  2213.7
   194.1 2201.99   227.4  2179.6   322.1 2188.74   354.4 2181.56   378.4 2174.03
   408.2 2174.94   413.9 2174.23  419.91 2171.04   425.6 2170.02   432.52171.077
   455.8 2174.22   589.4 2176.41   619.5 2178.74     681 2178.85   704.2 2181.63
   721.8  2190.6   758.6 2216.54   782.1 2229.27   803.5 2237.61   832.1 2246.08
   852.5 2256.48   863.4 2258.38   872.9  2265.7   885.2 2272.23   916.3 2284.89
#Mann= 9 ,-1,0
       0      .1       0     150     .06       0   357.4     .05       0
  419.91    .045       0   432.5     .05       0  460.27      .1       0
  480.27     .05       0  568.71     .06       0  679.29      .1       0
Bank Sta=419.91,432.5
XS Rating Curve= 0 ,0
Exp/Cntr(USF)=0,0
Exp/Cntr=0.3,0.1

Type RM Length L Ch R = 1 ,4560    ,211.5,212.9,214.3
XS GIS Cut Line= 6
2305679.70304232703862.6946617662305457.68577036703911.875703024
2305474.54784165704073.4705528692305401.47886607704225.229194462
2305401.47886607704275.8154083272305100.77192809 704337.64300305
#Sta/Elev= 30
       0 2280.17   122.4 2221.03   130.6 2214.57   142.9 2214.55   149.3 2212.88
   167.5 2201.93   212.6 2171.82   227.4 2170.34   398.8 2173.63   403.8 2173.41
  409.56 2170.51   414.2 2169.38   420.52170.518   427.8  2172.4   447.7 2173.41
   554.2  2176.3   594.7 2176.07   628.5 2178.78   655.6 2178.47   684.1 2181.72
   692.3 2185.02   726.7 2209.05   753.8 2224.53   782.1 2235.98   818.2  2246.2
   831.1 2253.54   839.3 2254.69     852 2262.84   880.1 2277.03   916.3 2290.02
#Mann= 9 ,-1,0
       0      .1       0     130     .06       0   227.4     .05       0
   257.4     .06       0  372.13     .05       0  409.56    .045       0
   420.5     .05       0  578.71     .06       0  649.29      .1       0
#XS Ineff= 2 , 0
           394.7 2202.02
Permanent Ineff=
       F       F
Bank Sta=409.56,420.5
XS Rating Curve= 0 ,0
Exp/Cntr(USF)=0,0
Exp/Cntr=0.3,0.1

Type RM Length L Ch R = 1 ,4347    ,122.8,126.6,128.9
XS GIS Cut Line= 4
 2305675.2897942703840.9183255842305352.04388761703902.380575429
2305260.98870265704007.0940381292305081.15471237704041.239732488
#Sta/Elev= 30
       0 2281.53    43.9 2260.98   117.2 2223.73   129.4 2214.32   133.5 2213.32
   145.7 2213.01   149.8  2211.4   167.1 2196.66   182.3 2185.77   194.5 2177.53
   204.7 2173.27   218.4 2170.92   247.5 2169.55   365.4 2168.48   377.6 2168.05
   383.52166.272   389.8 2164.87   394.7 2166.26     402 2168.45     433  2170.6
   455.7 2170.96   467.8 2175.62   494.2 2194.88   518.2  2210.7   542.1 2223.32
   558.2 2230.51   572.9 2235.53   598.9 2242.48   641.4 2248.21   650.9 2250.31
#Mann= 6 ,-1,0
       0      .1       0     120     .06       0     220     .05       0
   383.5    .045       0   394.7     .05       0   467.8      .1       0
Bank Sta=383.5,394.7
XS Rating Curve= 0 ,0
Exp/Cntr(USF)=0,0
Exp/Cntr=0.3,0.1

Type RM Length L Ch R = 1 ,4220    ,35.8,35.7,35.7
XS GIS Cut Line= 3
2305587.63765655 703748.24284688 2305421.5753796 703776.80132763
 2305078.8736106703909.016516285
#Sta/Elev= 30
       0 2246.66    56.3 2221.28    68.5 2212.44    84.7 2212.07    96.9 2205.98
   113.1 2199.74   129.3 2185.42   145.6 2184.45   153.7 2178.69   165.9 2172.06
   178.6  2167.9   187.2 2166.92   234.3 2166.13   336.9 2166.38  343.982164.195
   350.1 2162.69   358.5 2163.23  359.642164.117   367.2 2170.72   375.8 2176.68
   383.3 2184.58   388.7  2188.9   392.9 2190.35   402.9 2191.11     414 2197.91
   427.2 2202.61   435.8 2205.19   457.3 2208.65   491.6 2211.82   535.8 2221.93
#Mann= 8 ,-1,0
       0      .1       0      30     .06       0     130     .05       0
   238.5     .06       0   338.5     .05       0  343.98    .045       0
  359.64     .05       0   448.5      .1       0
Bank Sta=343.98,359.64
XS Rating Curve= 0 ,0
Exp/Cntr(USF)=0,0
Exp/Cntr=0.3,0.1

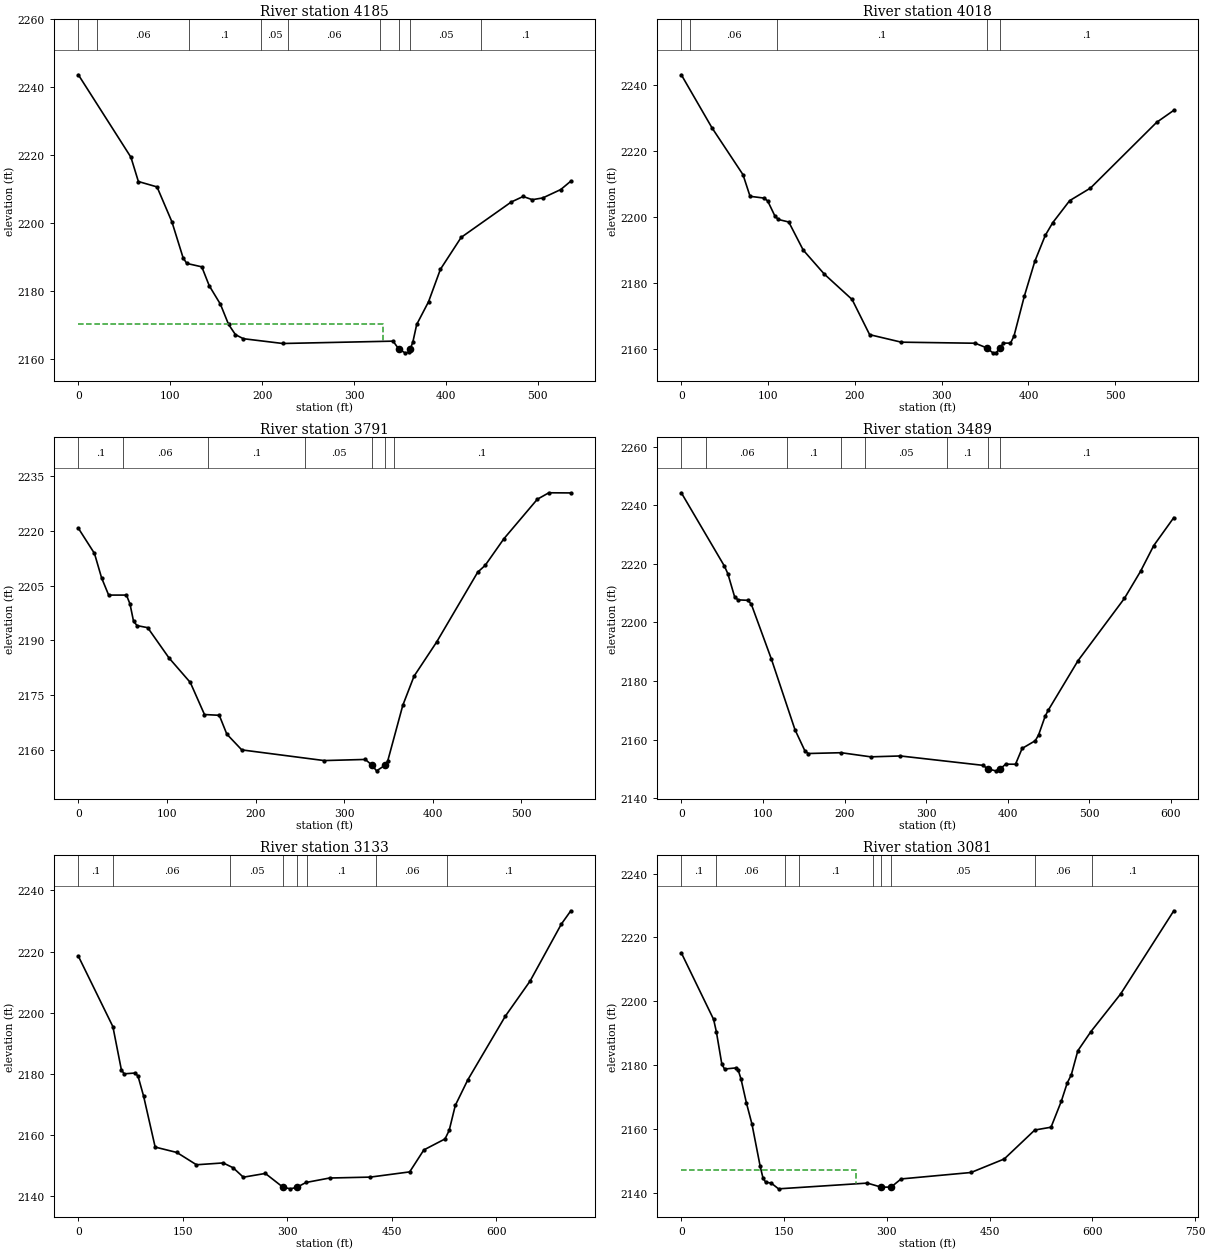
Type RM Length L Ch R = 1 ,4185    ,165.5,166.8,168.1
XS GIS Cut Line= 3
2305576.50364462703714.2326226472305410.44136767703742.791103397
2305067.73959867703875.006292053
#Sta/Elev= 30
       0 2243.71    57.2 2219.44    65.3  2212.3    85.6 2210.71   101.8 2200.43
     114 2189.82     118 2188.19   134.3 2187.19   142.4 2181.63   154.6 2176.17
   163.4 2170.26   170.9 2167.24   179.5 2166.04   222.4 2164.63   342.4 2165.32
   348.4 2163.09   355.3 2161.88   359.6 2162.01  361.242163.123   363.9 2165.01
   368.1 2170.22     381 2176.92   393.9 2186.46   416.5 2195.86     471 2206.27
   483.9 2207.89   493.9 2206.95   505.3 2207.47   524.8 2209.93   535.8 2212.41
#Mann= 9 ,-1,0
       0      .1       0      20     .06       0     120      .1       0
   198.5     .05       0   228.5     .06       0   328.5     .05       0
   348.4    .045       0  361.24     .05       0   438.5      .1       0
#XS Ineff= 2 , 0
          331.07 2170.25
Permanent Ineff=
       F       F
Bank Sta=348.4,361.24
XS Rating Curve= 0 ,0
Exp/Cntr(USF)=0,0
Exp/Cntr=0.3,0.1

Type RM Length L Ch R = 1 ,4018    ,228.2,227.3,225.7
XS GIS Cut Line= 3
 2305562.2782194703586.6122885452305183.06405536703649.743366931
2305000.37944893703661.507062138
#Sta/Elev= 30
       0 2242.95    35.3 2226.95    71.1 2212.77    79.2 2206.25    95.4 2205.71
    99.5 2204.86   107.6 2200.43   111.6 2199.27   123.8 2198.49   140.5    2190
   164.8 2182.75   196.8 2175.09     217 2164.47   253.5  2162.2   338.7 2161.88
   351.7  2160.5     359 2158.98     363 2159.06   367.1 2160.43   371.1 2161.92
   379.3 2161.91   383.3 2164.01   395.3 2176.13   407.4 2186.66   419.4 2194.45
     428 2198.29   447.5 2204.94   471.5 2208.74   547.7 2228.58   567.5 2232.22
#Mann= 5 ,-1,0
       0      .1       0      10     .06       0     110      .1       0
   351.7    .045       0   367.1      .1       0
Bank Sta=351.7,367.1
XS Rating Curve= 0 ,0
Exp/Cntr(USF)=0,0
Exp/Cntr=0.3,0.1

Type RM Length L Ch R = 1 ,3791    ,298.5,302.1,305.1
XS GIS Cut Line= 3
2305506.33456119703352.2374724212305360.60015647703360.810084464
2304972.68946155 703493.68557112
#Sta/Elev= 30
       0 2220.77    18.2 2213.84    26.2 2207.16    34.2 2202.41    54.3 2202.41
    58.3 2199.97    62.3 2195.23    66.3 2194.03    78.3 2193.46   102.3 2185.16
   126.4 2178.41   142.4 2169.61   159.1  2169.4   167.6 2164.24   184.5  2159.9
   277.5 2156.97     324 2157.28  331.292155.748   336.7 2154.15  346.642155.745
   349.4 2156.97   366.3 2172.15     379 2180.14   404.4 2189.48   450.9 2208.71
   459.3 2210.57   480.4 2217.87   518.2 2228.73   531.2  2230.5     556 2230.46
#Mann= 7 ,-1,0
       0      .1       0      50     .06       0  145.99      .1       0
  255.99     .05       0  331.29    .045       0  346.64     .05       0
  355.99      .1       0
Bank Sta=331.29,346.64
XS Rating Curve= 0 ,0
Exp/Cntr(USF)=0,0
Exp/Cntr=0.3,0.1

Type RM Length L Ch R = 1 ,3489    ,359.6,355.4,341
BEGIN DESCRIPTION:
Structure XS 4
END DESCRIPTION:
XS GIS Cut Line= 3
2305483.59591965703133.1093754912305342.14782095 703167.39982366
 2304887.7993827703109.534692374
#Sta/Elev= 30
       0 2244.26    52.9 2219.18      57 2216.64    65.3 2208.76    69.4 2207.69
    81.7 2207.54    85.8  2206.2   110.5 2187.39   139.3 2163.36   151.6 2156.05
   155.6 2155.23   195.9  2155.5   232.2 2154.09   268.5 2154.39   369.3  2151.2
   376.3 2149.91   385.4 2149.31   390.72149.915   397.5 2151.59   409.6 2151.57
   417.7 2156.96   433.8 2159.59   437.9 2161.58   445.9 2167.94   449.7    2170
   486.2 2186.92   543.1 2208.21   562.9 2217.47     579 2226.22   603.6 2235.78
#Mann= 8 ,-1,0
       0      .1       0      30     .06       0     130      .1       0
  195.55     .06       0  225.55     .05       0  325.55      .1       0
   376.3    .045       0   390.7      .1       0
Bank Sta=376.3,390.7
XS Rating Curve= 0 ,0
Exp/Cntr(USF)=0,0
Exp/Cntr=0.3,0.1

Type RM Length L Ch R = 1 ,3133    ,53.8,51.8,55.9
BEGIN DESCRIPTION:
Structure XS 3
END DESCRIPTION:
XS GIS Cut Line= 6
2305409.72863224702655.7186990372305299.62922559702662.046251143
2305275.58452759702817.704032953  2305228.760642702891.103637384
2305054.12020387  702886.04159572304899.72793248702963.237731394
#Sta/Elev= 30
       0 2218.51    49.6 2195.43    61.7 2181.39    65.7 2179.99    81.7 2180.26
    85.7 2179.23    93.7 2172.69   110.3 2156.02   141.5 2154.25   169.6 2150.23
     208 2150.83   222.3 2149.24   236.9 2146.16   268.5 2147.39   293.8 2142.89
   304.6 2142.35   314.1 2142.89   326.9 2144.43   360.7 2145.89   419.2 2146.19
   475.8  2147.9   496.1 2155.08   526.5 2158.68   532.5 2161.46   541.3 2169.66
   559.2    2178   613.1 2198.85   648.7 2210.36   693.6 2229.01   707.2 2233.36
#Mann= 8 ,-1,0
       0      .1       0      50     .06       0  218.02     .05       0
   293.8    .045       0   314.1     .05       0  328.51      .1       0
  427.64     .06       0  530.08      .1       0
Bank Sta=293.8,314.1
XS Rating Curve= 0 ,0
Exp/Cntr(USF)=0,0
Exp/Cntr=0.3,0.1

Type RM Length L Ch R = 1 ,3081    ,233.3,242.5,248
BEGIN DESCRIPTION:
Structure XS 2
END DESCRIPTION:
XS GIS Cut Line= 6
2305407.19761139702634.2050218762305265.46044422702640.532573982
   2305252.80534702768.3491265262305197.12288147702858.200366433
 2305037.6685684702836.6866892722304887.07282827702935.396502127
#Sta/Elev= 30
       0 2215.15    47.1 2194.31    51.1 2190.49    59.1 2180.33    63.1 2178.74
    79.1 2179.09    83.1 2178.36    87.1 2175.65    95.1 2168.06   103.1 2161.51
   115.1 2148.28   119.1 2144.71   123.1 2143.28   131.2 2143.02   141.9 2141.21
   271.5 2143.01   291.8 2141.74   306.22141.758   320.8 2144.31   422.9 2146.33
   471.4 2150.57     516 2159.64   539.7 2160.52   554.7 2168.66   563.3 2174.37
   569.3 2176.95   578.8 2184.47     598  2190.5   641.3 2202.27   718.9 2228.33
#Mann= 9 ,-1,0
       0      .1       0      50     .06       0  151.88     .05       0
  171.88      .1       0  280.33     .05       0   291.8    .045       0
   306.2     .05       0  516.22     .06       0  598.79      .1       0
#XS Ineff= 2 , 0
          255.13 2147.11
Permanent Ineff=
       F       F
Bank Sta=291.8,306.2
XS Rating Curve= 0 ,0
Exp/Cntr(USF)=0,0
Exp/Cntr=0.3,0.1

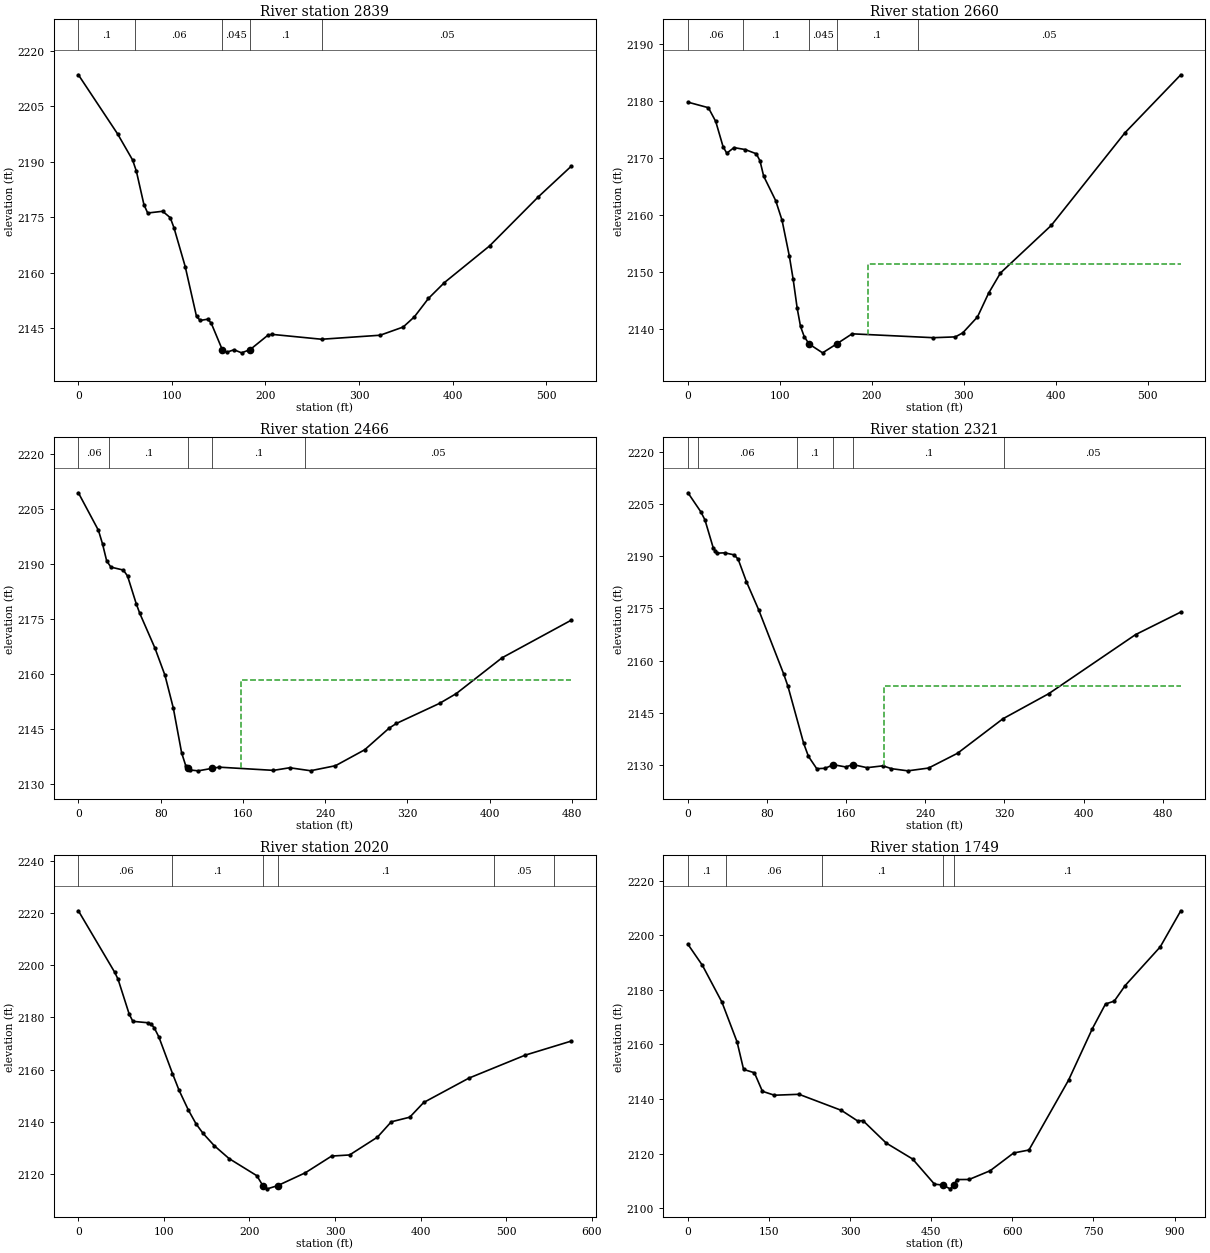
Type RM Length L Ch R = 1 ,2839    ,178.3,178.4,177.5
BEGIN DESCRIPTION:
Structure XS 1
END DESCRIPTION:
XS GIS Cut Line= 2
2305421.95401697702585.4386467222304897.24963733702538.595001266
#Sta/Elev= 30
       0 2213.56    41.9 2197.56      58 2190.47      62 2187.45    70.1 2178.38
    74.1 2176.13    90.1  2176.6    98.2 2174.87   102.2 2172.13   114.2 2161.63
   126.3 2148.11   130.3 2147.04   138.3 2147.38     142 2146.31   153.82139.146
   158.4 2138.42   166.4  2139.1   174.5 2138.27  183.622139.152   202.6 2143.04
   206.6 2143.28     260 2141.95   322.6 2143.04   347.2 2145.26   359.2 2148.03
   374.2    2153   391.3  2157.3   439.5 2167.21   491.7 2180.52   526.8 2188.79
#Mann= 5 ,-1,0
       0      .1       0      60     .06       0   153.8    .045       0
  183.62      .1       0     260     .05       0
Bank Sta=153.8,183.62
XS Rating Curve= 0 ,0
Exp/Cntr(USF)=0,0
Exp/Cntr=0.3,0.1

Type RM Length L Ch R = 1 ,2660    ,196.9,194.1,191.3
XS GIS Cut Line= 2
2305414.28036118 702404.59831554 2304879.6919013702369.155809039
#Sta/Elev= 30
       0 2179.85    22.2 2178.88    30.2 2176.47    38.2 2172.03    42.2 2170.89
    50.1 2171.87    62.2 2171.53    74.3 2170.79    78.3 2169.56    82.3 2166.87
    95.4 2162.56   102.3 2159.12   110.3 2152.77   114.4 2148.74   118.8 2143.63
   122.4 2140.46   126.4 2138.69   131.7 2137.38   146.4 2135.83   161.7  2137.4
   178.5 2139.17   266.7 2138.49   290.7 2138.63   298.8 2139.34   314.8 2142.14
   326.8 2146.28   339.8 2149.86     395 2158.21   475.1 2174.47   535.8 2184.66
#Mann= 5 ,-1,0
       0     .06       0      60      .1       0   131.7    .045       0
   161.7      .1       0     250     .05       0
#XS Ineff= 2 , 0
                          195.35         2151.38
Permanent Ineff=
       F       F
Bank Sta=131.7,161.7
XS Rating Curve= 0 ,0
Exp/Cntr(USF)=0,0
Exp/Cntr=0.3,0.1

Type RM Length L Ch R = 1 ,2466    ,147.3,145.2,143.7
XS GIS Cut Line= 2
2305383.40565194702184.4247556022304909.59855023702256.179196486
#Sta/Elev= 30
       0 2209.51    19.5 2199.26    23.5 2195.54    27.5 2190.94    31.6 2189.22
    43.7 2188.41    47.8  2186.8    56.2 2179.27    59.7  2176.6    74.5 2167.08
    84.2 2159.68    92.3 2150.76   100.4 2138.52   104.4    2135  106.932134.301
   108.5 2133.84   116.5  2133.6     130 2134.28     137  2134.6   189.7 2133.73
   205.5 2134.44   225.8 2133.63     250    2135   278.4 2139.35   302.1 2145.24
   309.2 2146.53   351.2 2152.02   367.4 2154.68   411.9 2164.45   479.2 2174.72
#Mann= 5 ,-1,0
       0     .06       0      30      .1       0  106.93    .045       0
     130      .1       0     220     .05       0
#XS Ineff= 2 , 0
                          158.48         2158.28
Permanent Ineff=
       F       F
Bank Sta=106.93,130
XS Rating Curve= 0 ,0
Exp/Cntr(USF)=0,0
Exp/Cntr=0.3,0.1

Type RM Length L Ch R = 1 ,2321    ,298.6,300.7,300.5
XS GIS Cut Line= 2
2305368.59918001702019.2756456312304892.51415954702166.201405536
#Sta/Elev= 30
       0 2208.25      13 2202.79    17.2 2200.44    25.6 2192.38    27.5 2191.62
    29.7 2190.89      37 2190.98    46.5 2190.41    50.7 2189.19    59.1  2182.7
    71.6 2174.52    96.7  2156.2     101 2152.68     117 2136.18   121.8 2132.45
   130.2  2128.9   138.6 2129.01     147 2130.04   159.5  2129.4  166.742130.082
     181 2129.19   197.2 2129.72   205.6 2128.91   222.3 2128.28   243.2 2129.08
   272.5 2133.33   318.4 2143.25   364.6 2150.45   452.5 2167.46   498.2 2173.94
#Mann= 6 ,-1,0
       0      .1       0      10     .06       0     110      .1       0
     147    .045       0  166.74      .1       0     320     .05       0
#XS Ineff= 2 , 0
                          198.19         2152.76
Permanent Ineff=
       F       F
Bank Sta=147,166.74
XS Rating Curve= 0 ,0
Exp/Cntr(USF)=0,0
Exp/Cntr=0.3,0.1

Type RM Length L Ch R = 1 ,2020    ,279.7,271,260.4
BEGIN DESCRIPTION:
Structure XS 4
END DESCRIPTION:
XS GIS Cut Line= 4
2305319.11220082701744.5633603182305152.20269854 701812.94865751
2305057.66326952701826.7915105622304855.65208754702048.695488675
#Sta/Elev= 30
       0  2220.9    42.6 2197.25    46.4 2194.64    59.4 2181.29    63.7 2178.52
      81 2177.99    85.3 2177.36    88.6 2176.08      94  2172.6     110 2158.52
   117.7 2152.09   128.4 2144.63   137.6 2139.19   145.8 2135.56   158.8 2130.87
   176.1 2125.93   208.6 2119.35   215.9 2115.39   220.8 2114.32     233 2115.56
   265.3 2120.48     296 2126.88     317 2127.31   349.5 2134.12   365.7 2140.01
   387.3 2141.78   403.6 2147.42   456.4 2156.75   522.2 2165.56     576 2170.95
#Mann= 6 ,-1,0
       0     .06       0     110      .1       0   215.9    .045       0
     233      .1       0  485.92     .05       0  555.92      .1       0
Bank Sta=215.9,233
XS Rating Curve= 0 ,0
Exp/Cntr(USF)=0,0
Exp/Cntr=0.3,0.1

Type RM Length L Ch R = 1 ,1749    ,70.5,71.1,70.8
BEGIN DESCRIPTION:
Structure XS 3
END DESCRIPTION:
XS GIS Cut Line= 5
2305231.07823742701252.8170408672305093.35727018701251.678851055
2305015.96036296701549.8845817872304957.91268255701693.296498093
2304650.60143333701739.962280383
#Sta/Elev= 30
       0 2196.69    26.9 2188.93    62.9 2175.48    90.9  2160.9   102.9 2150.84
   122.9 2149.61   137.7 2142.82   159.9 2141.38   205.4 2141.72   283.9 2135.82
   313.8 2131.96   323.7 2132.07   366.6 2123.86   415.5    2118   455.9 2108.79
   470.9 2108.46     485 2107.07  491.952108.463   497.3 2110.47   519.9  2110.5
   558.8  2113.7   602.3 2120.21   630.6  2121.3   703.8 2146.88   747.9 2165.78
   772.2 2174.82   788.4 2175.87   808.6 2181.59   873.4 2195.74   911.4 2208.98
#Mann= 5 ,-1,0
       0      .1       0      70     .06       0  247.73      .1       0
   470.9    .045       0  491.95      .1       0
Bank Sta=470.9,491.95
XS Rating Curve= 0 ,0
Exp/Cntr(USF)=0,0
Exp/Cntr=0.3,0.1