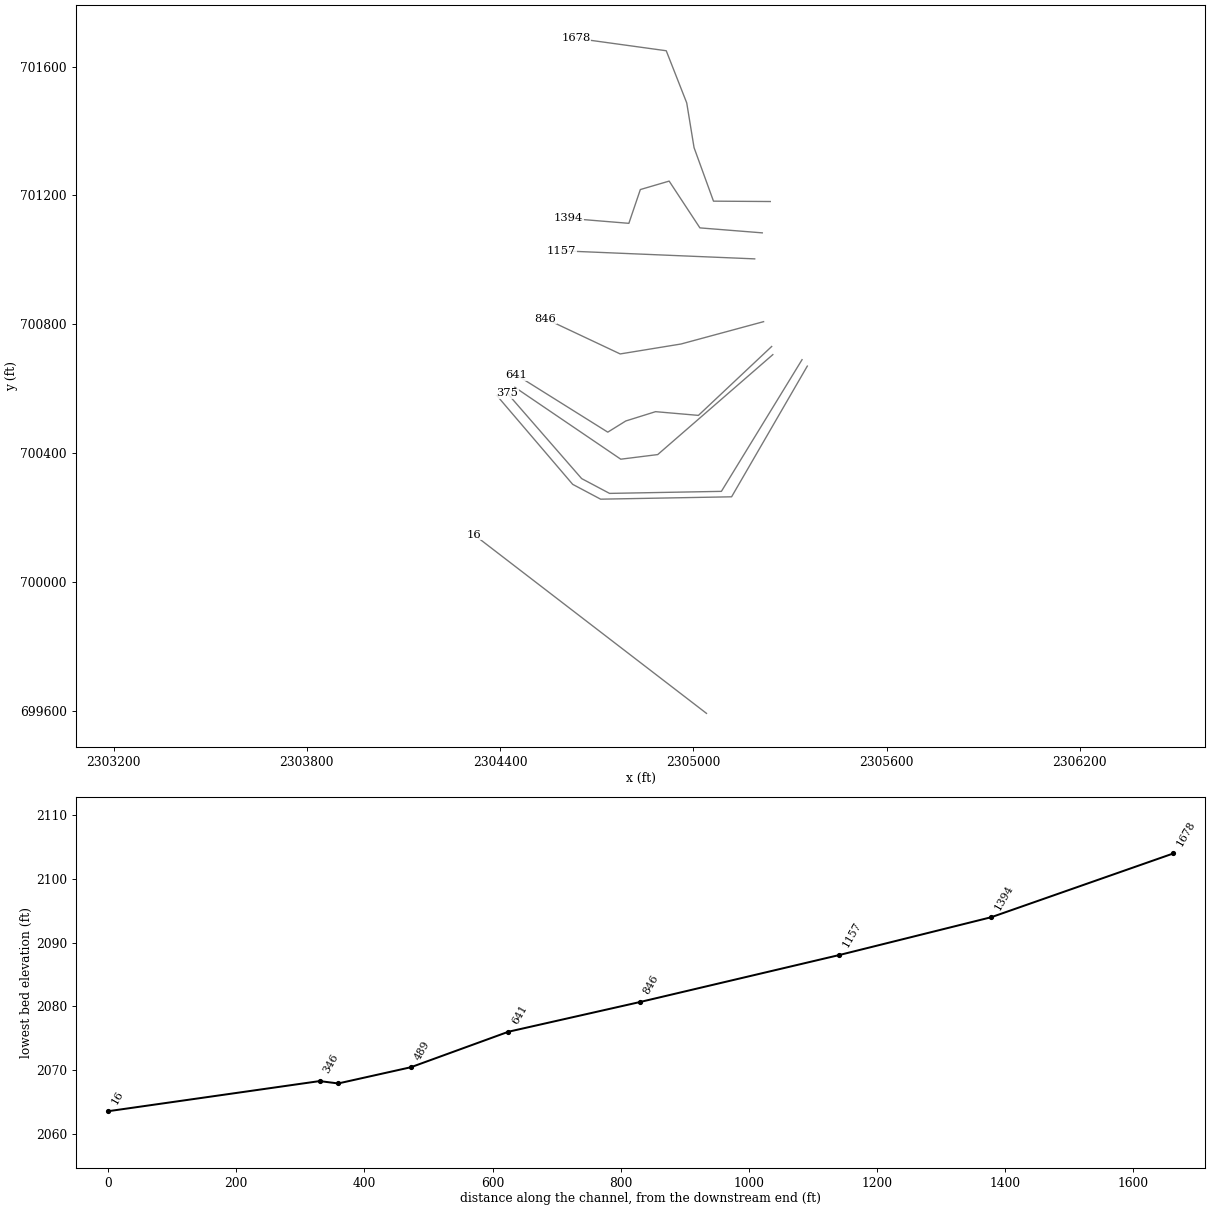
HEC-RAS study ISNERCK_U.prj: ISNERCK_U

--- ISNERCK_U.g01 (geometry) --- (continued)

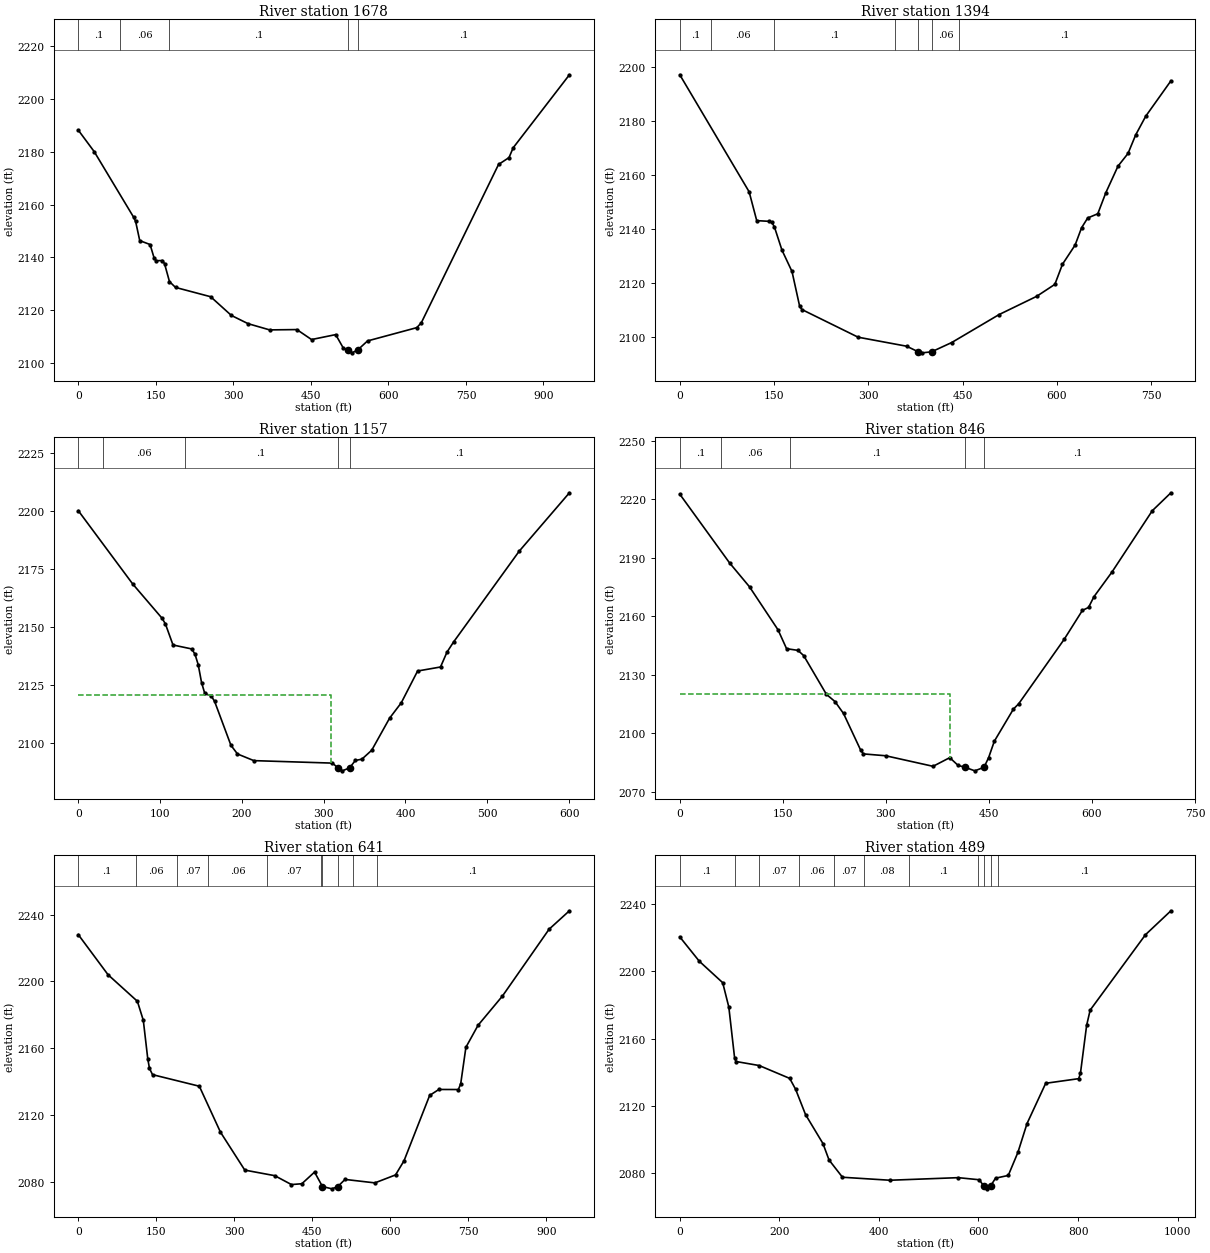
Type RM Length L Ch R = 1 ,1678    ,275,284.3,295.9
BEGIN DESCRIPTION:
Structure XS 2
END DESCRIPTION:
XS GIS Cut Line= 6
2305239.04556611701181.1110827142305062.62614525701182.249272526
2305002.30208522701348.4249850712304979.53828898701487.284142129
2304915.92965243 701649.288689422304636.43715852701687.839378236
#Sta/Elev= 30
       0  2188.1    30.9 2179.95   106.9 2155.25   110.9 2153.64   118.9 2146.35
   138.9 2144.88   146.9 2139.66   150.9 2138.76   162.9 2138.83   166.9 2137.61
   176.4 2130.88   188.1 2128.67   256.1 2125.15   296.1 2118.09   328.5 2114.97
   370.2 2112.62   422.9 2112.74   451.3 2108.97     498 2110.84   512.9 2105.69
   521.4  2105.1   529.9 2103.95   541.4 2105.19   559.6 2108.45   654.9 2113.47
   663.6 2115.29   813.1 2175.14   833.3 2177.72   841.4 2181.44   950.2 2209.02
#Mann= 5 ,-1,0
       0      .1       0      80     .06       0  176.42      .1       0
   521.4    .045       0   541.4      .1       0
Bank Sta=521.4,541.4
XS Rating Curve= 0 ,0
Exp/Cntr(USF)=0,0
Exp/Cntr=0.3,0.1

Type RM Length L Ch R = 1 ,1394    ,237.3,237.5,235.8
BEGIN DESCRIPTION:
Structure XS 1 (Also dirt road)
END DESCRIPTION:
XS GIS Cut Line= 6
 2305214.1485282 701083.793660852305020.45582055701099.262175697
2304924.95455498 701244.531706432304835.50618652701218.302485603
2304799.86134796701113.3856022962304612.22153743701128.854117143
#Sta/Elev= 30
       0 2197.13   110.3 2153.72   122.4 2143.01   142.4 2142.75   146.4 2142.38
   150.5 2140.69   162.5 2132.09   178.5 2124.14   190.6 2111.31   194.3 2110.02
   283.7 2099.76   360.8 2096.42   379.4 2094.34   385.6 2093.96   400.5 2094.34
   432.5 2097.78   507.9 2108.16   567.7 2114.93   596.6 2119.37   608.7 2126.83
   628.8 2133.94   639.1 2140.37   648.8 2143.99   664.9 2145.57   677.7 2153.39
     697 2163.22     713 2167.95   725.1 2174.79   741.1 2181.74   781.2 2194.88
#Mann= 7 ,-1,0
       0      .1       0      50     .06       0     150      .1       0
  343.12     .06       0   379.4    .045       0   400.5     .06       0
  444.56      .1       0
Bank Sta=379.4,400.5
XS Rating Curve= 0 ,0
Exp/Cntr(USF)=0,0
Exp/Cntr=0.3,0.1

Type RM Length L Ch R = 1 ,1157    ,310.8,311.1,318.7
BEGIN DESCRIPTION:
Structure XS 4
END DESCRIPTION:
XS GIS Cut Line= 2
2305190.60997219701003.0383851912304590.74144453701028.113275415
#Sta/Elev= 30
       0 2200.15    66.5 2168.57   102.5 2153.75   106.5 2151.35   115.8 2142.26
   138.6 2140.57   142.6 2138.36   146.6 2133.79   150.7 2126.07   154.6 2121.41
   162.6 2120.29   166.6 2117.99   186.6 2099.05   194.6  2095.3   214.6 2092.43
   310.7 2091.36   317.22089.367   322.7 2088.03  331.582089.289   338.7  2092.5
   346.7 2093.06   358.7  2096.9   380.5 2110.69   394.8 2117.33   414.8 2131.05
   442.8 2132.78   450.8 2139.23   458.8 2143.56   538.9 2182.64   600.4 2207.86
#Mann= 5 ,-1,0
       0      .1       0      30     .06       0     130      .1       0
   317.2    .045       0  331.58      .1       0
#XS Ineff= 2 , 0
          309.31 2120.55
Permanent Ineff=
       F       F
Bank Sta=317.2,331.58
XS Rating Curve= 0 ,0
Exp/Cntr(USF)=0,0
Exp/Cntr=0.3,0.1

Type RM Length L Ch R = 1 ,846     ,200.6,204.7,207.6
BEGIN DESCRIPTION:
Structure XS 3
END DESCRIPTION:
XS GIS Cut Line= 4
2305218.19130204700808.0831741262304961.82922141700738.691934257
2304772.93084621700707.8513832042304539.69917887700817.720846331
#Sta/Elev= 30
       0 2222.49    72.5 2187.24   101.5 2174.99     143 2152.95   155.4  2143.3
     172 2142.42   180.3 2139.76   213.4 2119.88   225.9 2116.18   238.3 2110.07
   263.2 2091.33   267.3 2089.35   299.7  2088.4   368.6 2082.99   392.9 2087.42
   405.1 2083.44   414.7 2082.55   429.4 2080.67  442.832082.507   449.5 2087.45
   457.8 2095.86   485.6 2112.34   493.2 2115.02   559.5 2148.11     586 2162.93
   594.9 2164.43   602.8 2169.94   629.1 2182.62   687.7 2214.01   714.8 2223.21
#Mann= 5 ,-1,0
       0      .1       0      60     .06       0     160      .1       0
   414.7    .045       0  442.83      .1       0
#XS Ineff= 2 , 0
          393.36    2120
Permanent Ineff=
       F       F
Bank Sta=414.7,442.83
XS Rating Curve= 0 ,0
Exp/Cntr(USF)=0,0
Exp/Cntr=0.3,0.1

Type RM Length L Ch R = 1 ,641     ,167.2,152.3,143.7
BEGIN DESCRIPTION:
Structure XS 2
END DESCRIPTION:
XS GIS Cut Line= 6
2305243.24924977700730.9817964942305015.80018575700517.025473564
2304882.80030934700528.5906802092304790.27865618700499.677663597
2304734.38015739700464.9820436622304451.03259459700642.315212217
#Sta/Elev= 30
       0 2227.98    57.2 2204.02   113.6 2188.15     125 2176.76   133.6 2153.68
   136.9 2147.99   142.7 2144.29   232.7 2137.37   273.3 2109.93   320.1 2087.23
   377.7  2083.9   409.8 2078.58   429.8 2079.08   454.2 2086.04  469.422077.421
   487.7 2076.03   498.9 2077.39   512.8 2081.66   570.2 2079.59   609.9 2084.35
   626.2 2092.78   675.5 2131.87   693.2 2135.43   730.7 2135.39   735.2 2138.82
   745.2 2160.65   768.6 2173.82   815.5  2191.3   905.1 2231.21   944.2 2242.24
#Mann= 10 ,-1,0
       0      .1       0     110     .06       0     190     .07       0
     250     .06       0  362.27     .07       0  467.22      .1       0
  469.42    .045       0   498.9      .1       0  527.22     .06       0
  574.15      .1       0
Bank Sta=469.42,498.9
XS Rating Curve= 0 ,0
Exp/Cntr(USF)=0,0
Exp/Cntr=0.3,0.1

Type RM Length L Ch R = 1 ,489     ,112.9,113.4,114.4
XS GIS Cut Line= 4
2305246.91899219700705.7221433182304889.41357226700395.337781599
2304774.68403921700380.9965899682304445.86100254700604.309431073
#Sta/Elev= 30
       0 2220.52    39.2 2206.03    86.2 2193.25    98.5 2178.74   110.1 2148.47
   112.9 2146.31   159.5 2143.91   220.8 2136.25   232.7 2129.74   252.6 2114.69
   287.6 2097.43   299.8 2087.66   326.8 2077.37   422.1 2075.59   559.3 2077.13
   601.8 2075.87  610.55  2072.1   616.3 2070.47   624.22072.141   634.2 2076.82
   659.8 2078.45   679.1 2092.12   697.5 2109.37     735 2133.34   801.2 2136.09
   804.8 2139.32   817.2 2167.84   824.3 2176.92   935.4 2221.82   986.5 2236.08
#Mann= 11 ,-1,0
       0      .1       0     110     .06       0     160     .07       0
     240     .06       0     310     .07       0     370     .08       0
     460      .1       0  599.07     .07       0  610.55    .045       0
   624.2     .07       0  639.07      .1       0
Bank Sta=610.55,624.2
XS Rating Curve= 0 ,0
Exp/Cntr(USF)=0,0
Exp/Cntr=0.3,0.1

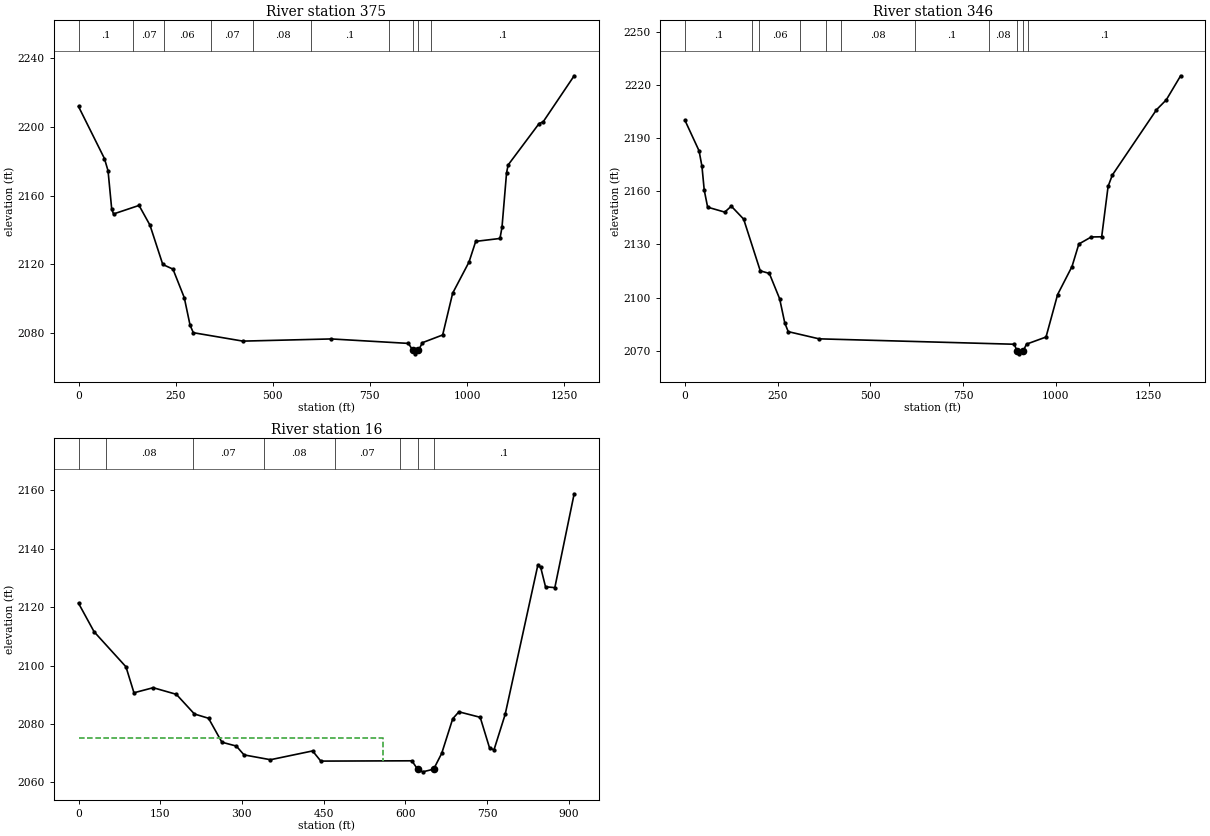
Type RM Length L Ch R = 1 ,375     ,28.9,29,29.1
BEGIN DESCRIPTION:
Structure XS 1
END DESCRIPTION:
XS GIS Cut Line= 5
2305337.61671117700690.0292132922305087.18577062700281.115905386
 2304739.8779623700274.7893911352304653.18716375700320.792257585
2304422.77175839700585.293206173
#Sta/Elev= 30
       0 2211.84    66.7 2181.57      76 2174.45    85.4 2152.27    90.1 2149.31
   155.8 2154.28   183.9 2142.81   216.9 2119.91   243.1 2117.22   272.2 2100.64
   287.1 2084.63   295.5 2080.23   423.1 2075.33   650.5  2076.6   849.2    2074
  860.68 2069.89   867.3 2067.93   874.6  2069.9   885.4 2074.44   937.3 2078.91
   963.1 2103.25  1005.1 2121.33  1022.4 2133.36  1084.8 2135.06    1090 2141.49
  1101.8  2173.3  1105.9 2177.85  1185.5 2201.91  1196.1 2202.95  1275.8 2229.71
#Mann= 10 ,-1,0
       0      .1       0     140     .07       0     220     .06       0
     340     .07       0     450     .08       0  599.51      .1       0
  799.51     .08       0  860.68    .045       0   874.6     .08       0
  906.87      .1       0
Bank Sta=860.68,874.6
XS Rating Curve= 0 ,0
Exp/Cntr(USF)=0,0
Exp/Cntr=0.3,0.1

Type RM Length L Ch R = 1 ,346     ,331,330.2,326
BEGIN DESCRIPTION:
Structure XS 1
END DESCRIPTION:
XS GIS Cut Line= 5
2305353.93801644700670.0585106762305118.87263835700264.218315262
2304712.15132185 700256.86743018 2304625.4605233700302.870296631
2304389.92326379700578.639324357
#Sta/Elev= 30
       0 2199.95      38 2182.78    45.8 2174.01    51.9 2160.64    61.1 2151.01
   107.3 2148.22   124.9 2151.58   158.2 2144.27     203 2115.12   227.5 2113.64
   255.3 2099.34   269.1 2085.74   278.4 2080.82   361.6 2076.76   887.8 2073.71
  896.15  2069.7   899.7  2068.3   911.5 2069.71     921 2073.77   973.6 2077.78
  1004.9 2101.76  1043.7 2117.55  1062.1 2130.23  1095.6  2134.2  1123.7 2134.31
    1141 2162.74  1152.4  2169.1  1271.5 2205.94  1297.9 2211.52  1336.6  2225.1
#Mann= 11 ,-1,0
       0      .1       0     180     .07       0     200     .06       0
     310     .08       0     380     .07       0     420     .08       0
     619      .1       0     819     .08       0  896.15    .045       0
   911.5     .08       0  925.79      .1       0
Bank Sta=896.15,911.5
XS Rating Curve= 0 ,0
Exp/Cntr(USF)=0,0
Exp/Cntr=0.3,0.1

Type RM Length L Ch R = 1 ,16      ,285.2,288.1,285.5
XS GIS Cut Line= 2
2305040.90855832699591.7251013272304319.45363373700146.106253908
#Sta/Elev= 30
       0 2121.34    28.6 2111.57    87.1 2099.56   101.8 2090.66   137.1  2092.4
   179.6 2090.13   212.8 2083.39   238.7 2081.93   263.2 2073.73   289.7 2072.41
   303.9 2069.38   352.4 2067.73   429.7 2070.74   444.8 2067.26     612 2067.36
  622.392064.503     632 2063.58   651.9 2064.49   666.8 2069.94     687 2081.78
   698.3 2084.14   737.4 2082.26   754.6 2071.75   762.7  2071.1   783.2 2083.23
   843.1  2134.3   848.4 2133.67   857.3 2126.97   874.4 2126.68   909.9 2158.83
#Mann= 8 ,-1,0
       0     .07       0      50     .08       0     210     .07       0
     340     .08       0     470     .07       0     590      .1       0
  622.39    .045       0   651.9      .1       0
#XS Ineff= 2 , 0
          558.07 2075.25
Permanent Ineff=
       F       F
Bank Sta=622.39,651.9
XS Rating Curve= 0 ,0
Exp/Cntr(USF)=0,0
Exp/Cntr=0.3,0.1
LCMann Table=0

Chan Stop Cuts=-1
Use User Specified Reach Order=0
Composite Channel Slope=5